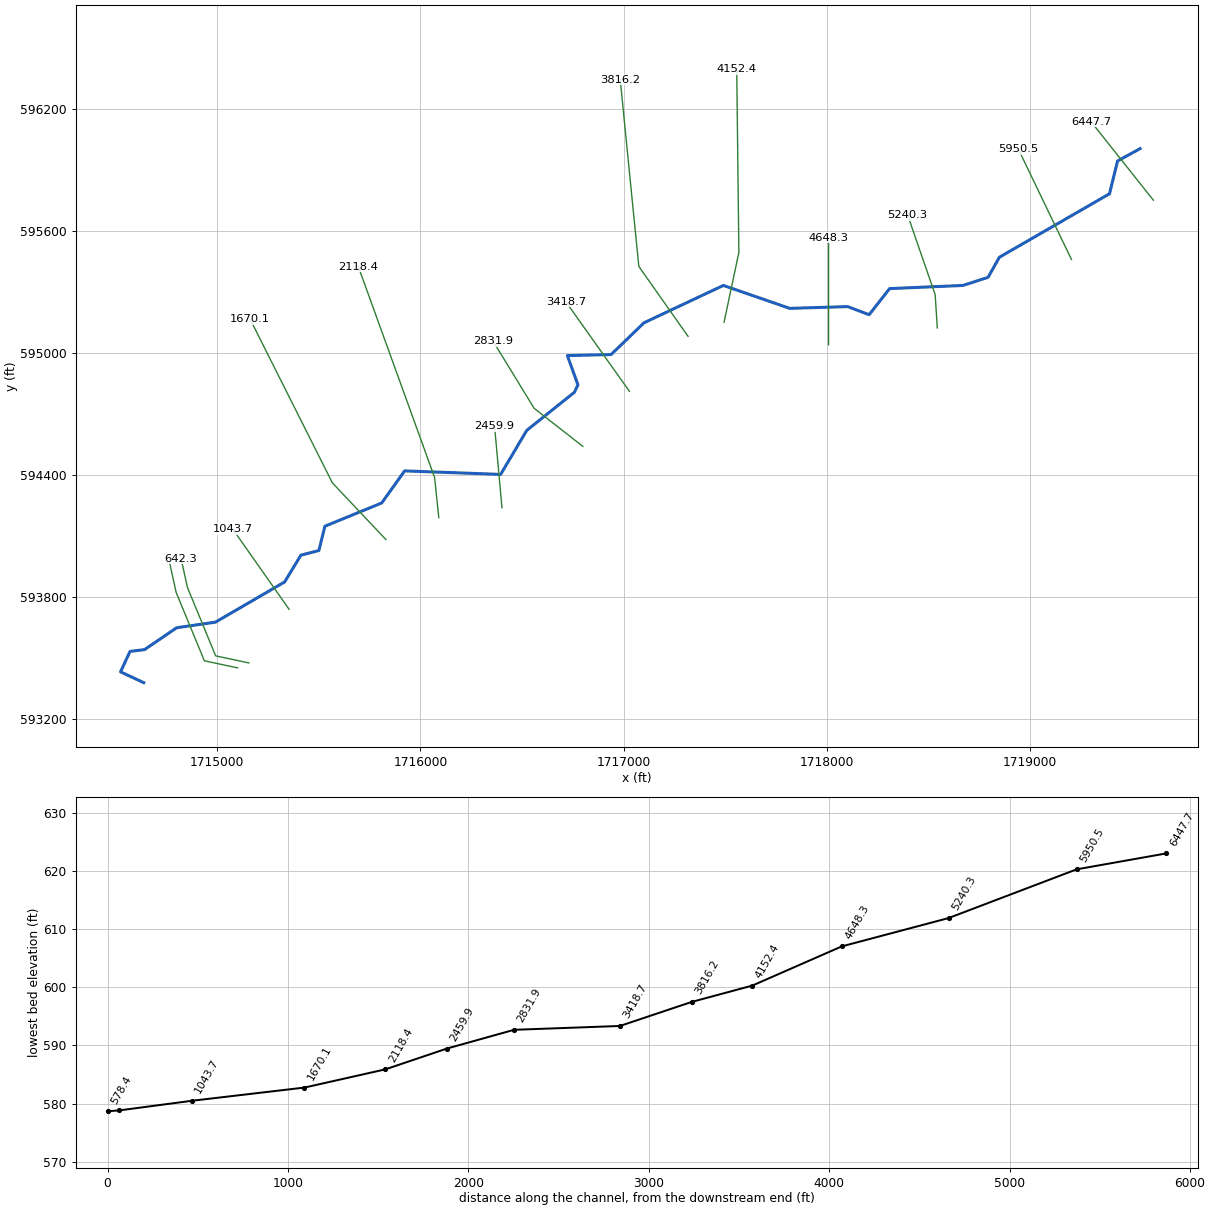
--- TurkeyBr.prj (project) ---

Proj Title=TurkeyBr
Current Plan=p01
Default Exp/Contr=0,0
English Units
Geom File=g01
Flow File=f01
Plan File=p01
BEGIN DESCRIPTION:
AMEC Environment & Infrastructure, 2013
Projection: NAD 1983 State Plane West Virginia South FIPS 4702 (US Feet)
Vertical Datum: NAVD 1988
END DESCRIPTION:
DSS Export Rating Curves= 0
DSS Export Rating Curve Sorted= 0
DSS Export Volume Flow Curves= 0
DXF OffsetX= 0
DXF OffsetY= 0
DXF ScaleX= 0
DXF ScaleY= 0

--- TurkeyBr.p01 (plan) ---

Plan Title=Floodplain
Program Version=4.00
Geom File=g01
Flow File=f01
K Sum by GR=0
Std Step Tol=0.01
Critical Tol=0.01
Num of Std Step Trials=20
Max Error Tol=0.3
Flow Tol Ratio=0.001
Split Flow NTrial=30
Split Flow Tol=0.02
Split Flow Ratio=0.02
Log Output Level=0
Friction Slope Method=1
Unsteady Friction Slope Method=2
Unsteady Bridges Friction Slope Method=1
Global Log Level=0
CheckData=False
Run HTab=0
Run UNet=0
Run PostProcess=0
UNET Theta=0
UNET Theta Warmup=0
UNET ZTol=0
UNET ZSATol=0
UNET MxIter=0
UNET MaxInSteps=0
UNET DtIC=0
UNET DtMin=0
UNET MaxCRTS=0
UNET WFStab=0
UNET SFStab=0
UNET WFX=0
UNET SFX=0
UNET DSS MLevel=0
UNET DZMax Abort=0
UNET Convert EG Bridges=0
UNET Use Existing IB Tables=0
UNET Froude Limit=0
UNET Froude Power=0
Write IC File=0
Echo Input=False
Echo Output=False
Write Detailed=0

--- TurkeyBr.f01 (steady flow) ---

Flow Title=USGS Regress. Eqn. (2010) - Western-Plateaus
Program Version=4.10
Number of Profiles= 1
Profile Names=P100yr
River Rch & RM=TurkeyBr,Main            ,6447.7
     880
River Rch & RM=TurkeyBr,Main            ,5950.5
     911
River Rch & RM=TurkeyBr,Main            ,4152.4
     964
River Rch & RM=TurkeyBr,Main            ,3816.2
    1421
River Rch & RM=TurkeyBr,Main            ,2831.9
    1434
River Rch & RM=TurkeyBr,Main            ,1043.7
    1551
River Rch & RM=TurkeyBr,Main            ,642.3
    1558
Boundary for River Rch & Prof#=TurkeyBr,Main            , 1
Up Type= 0
Dn Type= 3
Dn Slope=0.00376
DSS Import GetInterval= 0
DSS Import GetPeak= 0
DSS Import FillOption= 0

--- TurkeyBr.g01 (geometry) ---

Geom Title=USGS 3m DEM
Program Version=4.10

River Reach=TurkeyBr        ,Main
Reach XY= 30
     1719540.094      596006.808     1719429.546      595946.084
     1719389.827      595784.584      1718848.16      595472.084
     1718792.605      595373.125     1718669.341      595333.195
      1718308.23       595317.57     1718207.535      595189.098
     1718101.633      595229.028      1717816.91      595220.348
     1717490.522      595333.195     1717099.897      595149.167
     1716938.438      594992.917      1716723.16      594987.709
     1716775.244      594843.611     1716757.883      594807.153
     1716523.508      594619.653     1716395.035      594402.639
     1715922.813         594420.     1715809.966      594262.014
     1715530.452      594147.431     1715500.938      594027.639
     1715412.397       594005.07     1715332.535      593873.125
     1714992.258      593675.209     1714801.285      593647.431
     1714643.299      593539.792     1714572.119      593531.111
     1714525.244      593430.417     1714639.493      593376.993

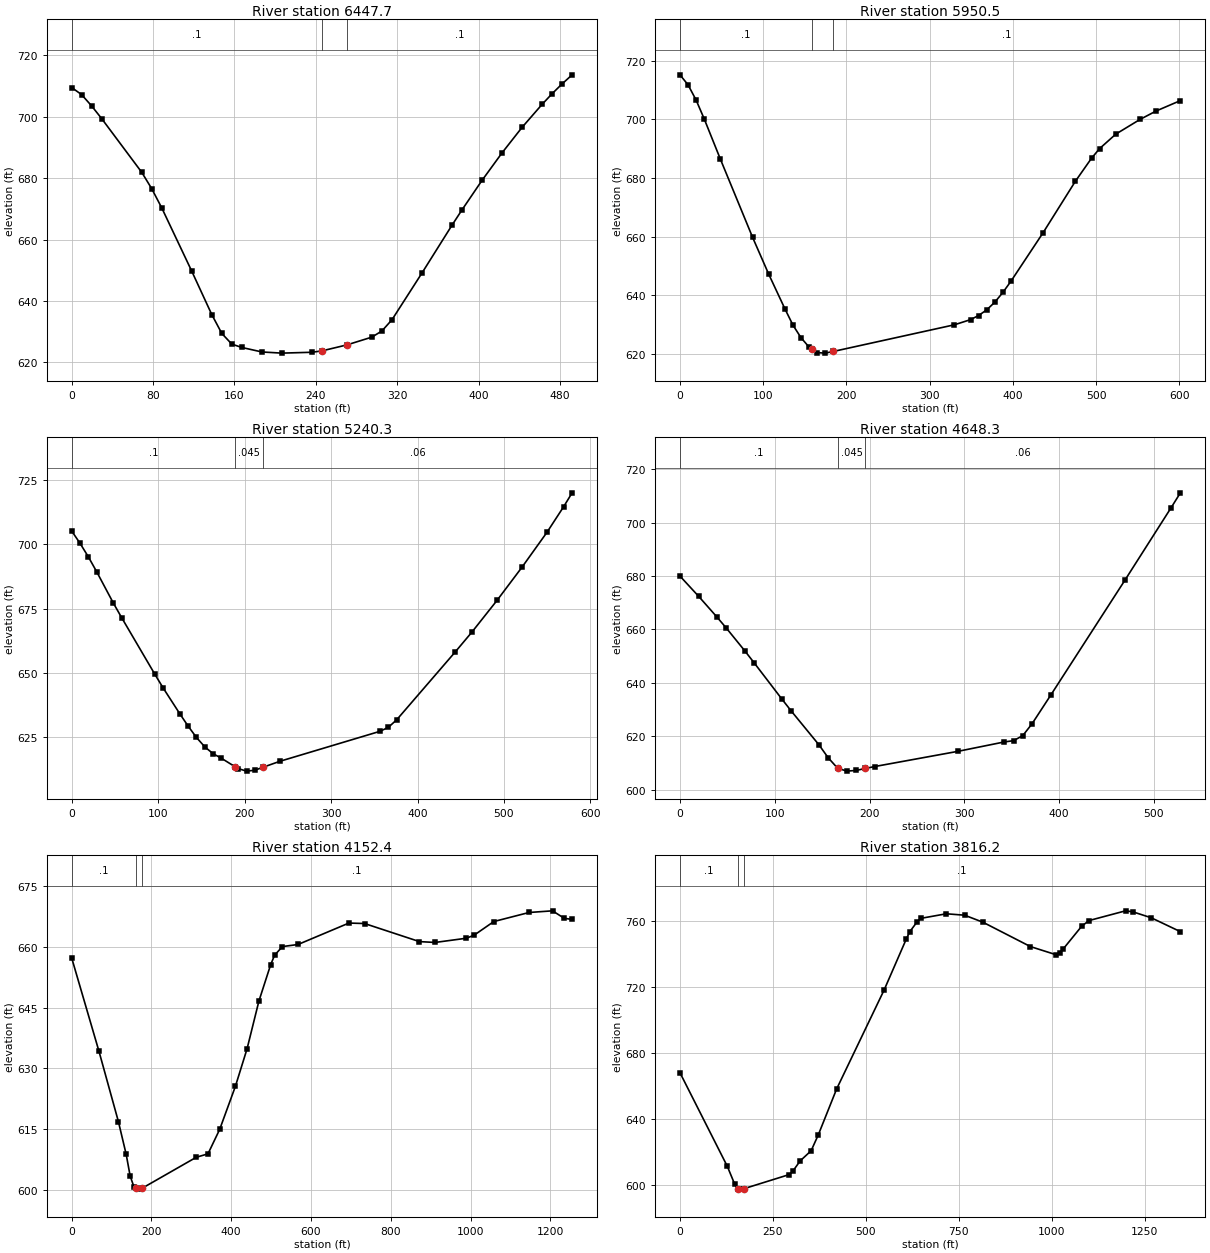
Type RM Length L Ch R = 1 ,6447.7  ,502.4,497.2,491.9
XS GIS Cut Line= 2
     1719605.533      595753.116     1719299.854      596138.614
#Sta/Elev= 30
       0  709.51     9.8  707.18    19.7  703.47    29.5  699.37    68.9  681.88
    78.7  676.55    88.6  670.27   118.1  649.65   137.8  635.51   147.6  629.41
   157.4  625.94   167.3  624.84     187  623.38   206.6     623   236.2  623.28
     246  623.73   270.5  625.67   295.2  628.22     305  630.22   314.9  633.87
   344.4   649.1   373.9  664.66   383.8  669.69   403.4  679.25   423.1  688.22
   442.8  696.53   462.5  704.03   472.3  707.48   482.1  710.67     492  713.64
#Mann= 3 , 0 , 0
       0      .1       0     246    .045       0   270.5      .1       0
Bank Sta=246,270.5
XS Rating Curve= 0 ,0
Exp/Cntr=0.3,0.1

Type RM Length L Ch R = 1 ,5950.5  ,712.7,710.2,707.5
XS GIS Cut Line= 2
     1719202.667      595461.328     1718942.125      596003.125
#Sta/Elev= 30
       0  715.24     9.7  711.82    19.4  706.62    29.1  700.22    48.5   686.5
    87.3  659.74   106.7  647.15   126.1  635.36   135.8  629.79   145.4  625.53
   155.2  622.28   158.9  621.57   164.8  620.43   174.5  620.26   184.2  620.83
   329.7  629.93   349.1  631.69   358.8   633.1   368.5  635.02   378.2  637.64
   387.9  640.96   397.6  644.78   436.4  661.42   475.1  678.94   494.5   686.8
   504.2  690.08   523.6     695   552.7  700.02   572.1   702.9   601.2  706.45
#Mann= 3 , 0 , 0
       0      .1       0   158.9    .045       0   184.2      .1       0
Bank Sta=158.9,184.2
XS Rating Curve= 0 ,0
Exp/Cntr=0.3,0.1

Type RM Length L Ch R = 1 ,5240.3  ,599.4,592,584.2
XS GIS Cut Line= 3
     1718542.789      595124.365     1718532.354      595287.605
     1718396.862      595680.065
#Sta/Elev= 30
       0  705.17     9.6  700.42    19.2  695.17    28.9  689.35    48.1  677.22
    57.7  671.55    96.2   649.5   105.8  644.18   125.1  634.14   134.7  629.35
   144.3  624.96     154  621.29   163.6  618.64   173.2  616.87   189.4   613.5
   192.5  612.88   202.2  611.88   211.8  612.22   221.5  613.41   240.8   615.7
   356.7  627.36   366.3  628.91     376  631.86   443.6  658.18   462.9  665.89
   491.9  678.19   520.8  691.09   549.8   704.7   569.1  714.66   578.8     720
#Mann= 3 , 0 , 0
       0      .1       0   189.4    .045       0   221.5     .06       0
Bank Sta=189.4,221.5
XS Rating Curve= 0 ,0
Exp/Cntr=0.3,0.1

Type RM Length L Ch R = 1 ,4648.3  ,500.6,496,491.2
XS GIS Cut Line= 2
     1718007.922      595040.958     1718007.872      595568.885
#Sta/Elev= 24
       0  679.98    19.6  672.45    39.1  664.62    48.9  660.53    68.4  652.01
    78.2  647.55   107.5  633.97   117.3  629.54   146.6  616.86   156.4  611.99
   166.2  608.14     176  607.01   185.8  607.27   195.6  608.01   205.3  608.72
   293.3  614.42   342.2  617.93     352  618.41   361.7  620.33   371.5  624.77
   391.1  635.42   469.3   678.4   518.2  705.62   527.9  711.13
#Mann= 3 , 0 , 0
       0      .1       0   166.2    .045       0   195.6     .06       0
Bank Sta=166.2,195.6
XS Rating Curve= 0 ,0
Exp/Cntr=0.3,0.1

Type RM Length L Ch R = 1 ,4152.4  ,317.1,336.1,355.1
XS GIS Cut Line= 3
     1717493.877      595152.052     1717566.782      595495.906
     1717556.277       596398.94
#Sta/Elev= 30
       0  657.21    68.4  634.22   117.2  616.88   136.7   608.8   146.5  603.55
   156.2  600.77   161.1  600.52     166  600.27   176.1  600.46   312.4  608.12
   341.7  608.96   371.1     615   410.4  625.58   439.8  634.88   469.3  646.57
   498.7  655.51   508.6  657.87   528.2  660.01   567.5  660.53   695.1  665.81
   734.3  665.69   871.8  661.24     911  661.03   989.6  662.07  1009.2  662.84
  1058.3  666.18  1146.6  668.41  1205.5  668.82    1235  666.97  1254.6  666.71
#Mann= 3 , 0 , 0
       0      .1       0   161.1    .045       0   176.1      .1       0
Bank Sta=161.1,176.1
XS Rating Curve= 0 ,0
Exp/Cntr=0.3,0.1

Type RM Length L Ch R = 1 ,3816.2  ,397.4,397.5,397.7
XS GIS Cut Line= 3
      1717316.75      595082.571     1717074.598      595427.102
     1716983.202      596346.787
#Sta/Elev= 30
       0  667.93   127.3  611.26   146.9  600.56   156.6  597.78   166.5  597.46
   171.6   597.7   293.8  606.28   303.6   608.4   323.2  614.58   352.6   620.7
   372.2   630.5   421.1  658.07   548.9  718.06   607.9  748.61   617.8  753.32
   637.4  759.24   647.2  761.38   716.1  764.16   765.2   763.3   814.4  759.06
   942.2   744.3    1011  739.38  1020.9  740.58  1030.7  742.99  1079.9  756.61
  1099.5  760.05  1197.8  765.95  1217.5  765.34  1266.7  761.76  1345.3  753.34
#Mann= 3 , 0 , 0
       0      .1       0   156.6    .045       0   171.6      .1       0
Bank Sta=156.6,171.6
XS Rating Curve= 0 ,0
Exp/Cntr=0.3,0.1

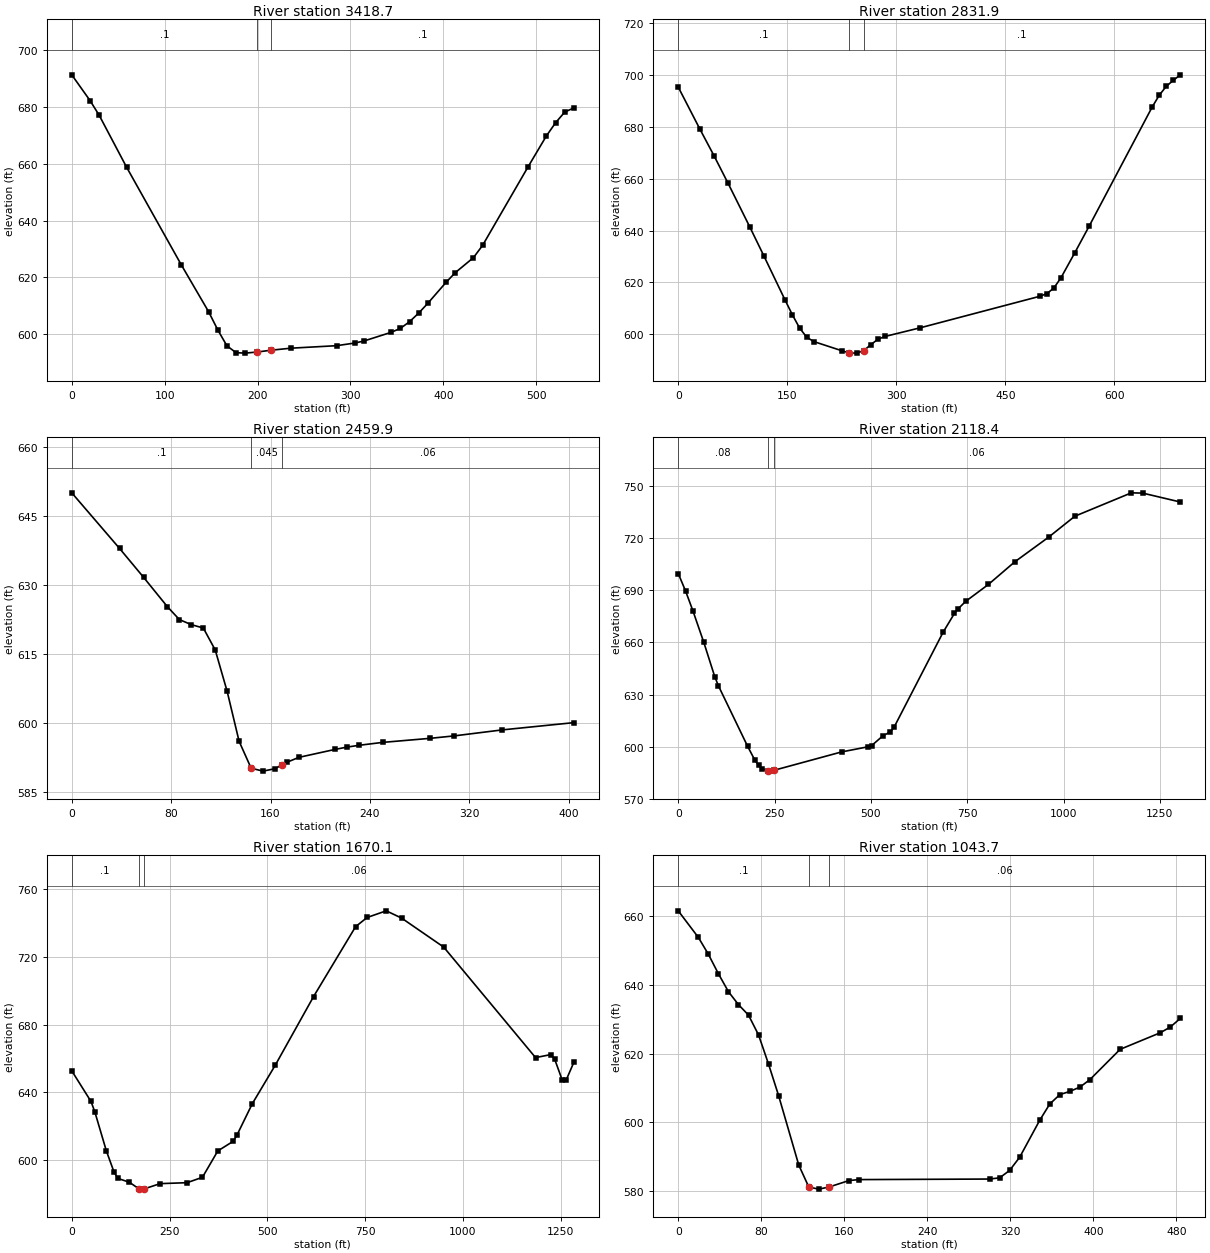
Type RM Length L Ch R = 1 ,3418.7  ,576.9,586.8,595.1
XS GIS Cut Line= 2
     1717028.499      594811.634     1716715.869      595252.702
#Sta/Elev= 30
       0  691.36    19.7  682.28    29.5  677.12      59  658.84     118  624.39
   147.4  607.88   157.3  601.45   167.1  595.88   176.9  593.49   186.8  593.33
   199.6  593.72   214.6  594.36   235.9  595.07   285.1  595.95   304.7  596.88
   314.6   597.6     344  600.67   353.9  602.06   363.7   604.4   373.5  607.42
   383.4  610.89     403  618.26   412.8  621.64   432.5  626.97   442.3  631.26
   491.5  659.06   511.1  669.87     521  674.51   530.8  678.25   540.6  679.71
#Mann= 3 , 0 , 0
       0      .1       0   199.6    .045       0   214.6      .1       0
Bank Sta=199.6,214.6
XS Rating Curve= 0 ,0
Exp/Cntr=0.3,0.1

Type RM Length L Ch R = 1 ,2831.9  ,390.9,372,352.1
XS GIS Cut Line= 3
     1716799.293      594540.702     1716559.624      594728.233
     1716358.147      595058.168
#Sta/Elev= 30
       0  695.39    29.4  679.38    49.1  668.96    68.7  658.18    98.2  641.54
   117.8  630.24   147.2  613.06   157.1  607.45   166.9  602.42   176.7  598.83
   186.5  597.14   225.8  593.53   235.6  592.74   245.4  592.67   255.2  593.61
     265  595.93   274.9  598.05   284.7  599.12   333.3  602.47   497.6  614.62
   507.3  615.63   516.9  617.82   526.6  621.73   545.9  631.52   565.3  641.61
   652.2   687.7   661.9  692.24   671.6  695.69   681.2  697.98   690.9  700.12
#Mann= 3 , 0 , 0
       0      .1       0   235.6    .045       0   255.2      .1       0
Bank Sta=235.6,255.2
XS Rating Curve= 0 ,0
Exp/Cntr=0.3,0.1

Type RM Length L Ch R = 1 ,2459.9  ,335.3,341.5,348.7
XS GIS Cut Line= 2
     1716401.474      594238.729     1716364.926      594641.293
#Sta/Elev= 24
       0     650    38.5  637.89    57.8  631.62      77  625.22    86.6  622.43
    96.2  621.32   105.9  620.59   115.5   615.8   125.1  606.79   134.7  595.95
   144.4  590.08     154  589.45   163.6  589.98   169.4  590.83   173.2  591.38
   182.9  592.45   211.7  594.16   221.4  594.67     231  595.06   250.2   595.7
   288.7  596.59     308  597.12   346.5  598.42   404.2     600
#Mann= 3 , 0 , 0
       0      .1       0   144.4    .045       0   169.4     .06       0
Bank Sta=144.4,169.4
XS Rating Curve= 0 ,0
Exp/Cntr=0.3,0.1

Type RM Length L Ch R = 1 ,2118.4  ,437.4,448.3,458.7
XS GIS Cut Line= 3
     1716090.792      594189.842     1716069.934      594387.812
      1715694.73      595426.265
#Sta/Elev= 30
       0   699.7      19  689.64    37.9  678.33    66.4  660.02    94.8  640.27
   104.3  635.01   180.1  600.15   199.1   592.1   208.8  589.18   218.6  587.22
   233.2  585.99   238.2  585.87   248.2  586.33   423.8  596.92   492.2  599.87
     502  600.59   531.3  606.21   550.8  608.52   560.6  611.32   687.6  665.91
     717  676.74   726.7  679.43   746.3  683.69   804.9  693.37   873.3  706.38
   961.2   720.6  1029.6  732.71  1176.2  746.17  1205.5  746.01  1303.2  740.88
#Mann= 3 , 0 , 0
       0     .08       0   233.2    .045       0   248.2     .06       0
Bank Sta=233.2,248.2
XS Rating Curve= 0 ,0
Exp/Cntr=0.3,0.1

Type RM Length L Ch R = 1 ,1670.1  ,628.9,626.3,622.6
XS GIS Cut Line= 3
     1715830.312      594082.148     1715567.293      594360.895
     1715163.354      595165.724
#Sta/Elev= 30
       0   652.7    49.1  634.61      59  628.41    88.4  605.38   108.1  592.82
   117.9  589.08   147.4   586.8   170.8  583.06   176.9  582.74   185.8  582.94
     226  585.99   294.8  586.55   334.1  589.74   373.4  605.33   412.6     611
   422.4  614.69   461.6  633.26   520.3  656.02   618.2  696.59   725.8  737.98
   755.2  743.39   804.1  747.33   843.3  743.04     951  725.89  1185.9  660.52
    1225  662.32  1234.8  659.58  1254.4  647.02  1264.2  647.27  1283.8  657.74
#Mann= 3 , 0 , 0
       0      .1       0   170.8    .045       0   185.8     .06       0
Bank Sta=170.8,185.8
XS Rating Curve= 0 ,0
Exp/Cntr=0.3,0.1

Type RM Length L Ch R = 1 ,1043.7  ,406.1,401.5,396.5
XS GIS Cut Line= 2
     1715354.515      593738.256     1715076.622      594134.175
#Sta/Elev= 30
       0  661.63    19.4  653.87      29  648.98    38.7  643.28    48.4  638.03
      58  634.28    67.7  631.21    77.4  625.42    87.1  616.83    96.7  607.73
   116.1  587.49   125.8  581.06   135.4  580.46   145.1  581.06   164.5  582.96
   174.1  583.24   299.9   583.4   309.6  583.75   319.2   585.9   328.9  589.74
   348.3  600.57     358  605.31   367.6  608.02   377.3  608.97     387  610.22
   396.6   612.4   425.7  621.23   464.4  626.07     474  627.72   483.7  630.25
#Mann= 3 , 0 , 0
       0      .1       0   125.8    .045       0   145.1     .06       0
Bank Sta=125.8,145.1
XS Rating Curve= 0 ,0
Exp/Cntr=0.3,0.1

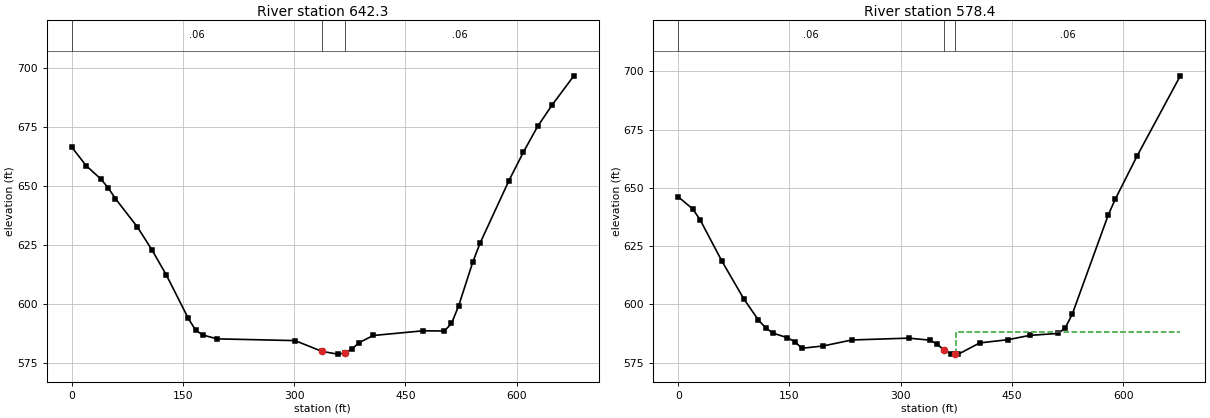
Type RM Length L Ch R = 1 ,642.3   ,64.5,63.9,63.9
XS GIS Cut Line= 4
     1715156.568      593474.274     1714993.324      593508.991
     1714854.364      593845.878     1714823.092      593988.276
#Sta/Elev= 30
       0  666.57    19.6  658.64    39.3  653.04    49.1  649.32    58.9  644.73
    88.4  632.75     108  623.08   127.6  612.33   157.1  593.99   166.9     589
   176.5  586.95   195.7  585.29   301.2  584.54   337.3  579.98   358.7  578.81
   368.3  579.29   377.9  581.01   387.5  583.67   406.6  586.71   473.8   588.7
   502.6  588.62   512.1  591.81   521.7  599.25     541  618.02   550.8     626
   589.6   652.4   609.1  664.48   628.5   675.5     648  684.53   677.1  696.81
#Mann= 3 , 0 , 0
       0     .06       0   337.3    .045       0   368.3     .06       0
Bank Sta=337.3,368.3
XS Rating Curve= 0 ,0
Exp/Cntr=0.3,0.1

Type RM Length L Ch R = 1 ,578.4   ,518.3,578.4,636.2
XS GIS Cut Line= 4
     1715100.999      593449.956     1714937.755      593484.673
     1714798.795       593821.56     1714767.523      593963.959
#Sta/Elev= 30
       0  646.16    19.6  640.95    29.4  636.37    58.9  618.57    88.4  602.39
     108  593.36   117.8  589.98   127.6   587.7   147.3   585.7   157.1     584
   166.9  581.18   195.7  582.19     234  584.74   310.8  585.53   339.5  584.66
   349.1  582.95   357.9  580.53   368.3  578.69   372.9  578.68   377.9  578.67
   406.6  583.49     445  584.87   473.8  586.71   512.1  587.55   521.7  589.79
   531.3  595.75   579.9  638.38   589.6  645.31   618.8  663.68   677.1  698.09
#Mann= 3 , 0 , 0
       0     .06       0   357.9    .045       0   372.9     .06       0
#XS Ineff= 2 , 0
       0                     375       0     588
Permanent Ineff=
       F       F
Bank Sta=357.9,372.9
XS Rating Curve= 0 ,0
Exp/Cntr=0.3,0.1

Chan Stop Cuts=-1
Use User Specified Reach Order=0
Composite Channel Slope=5